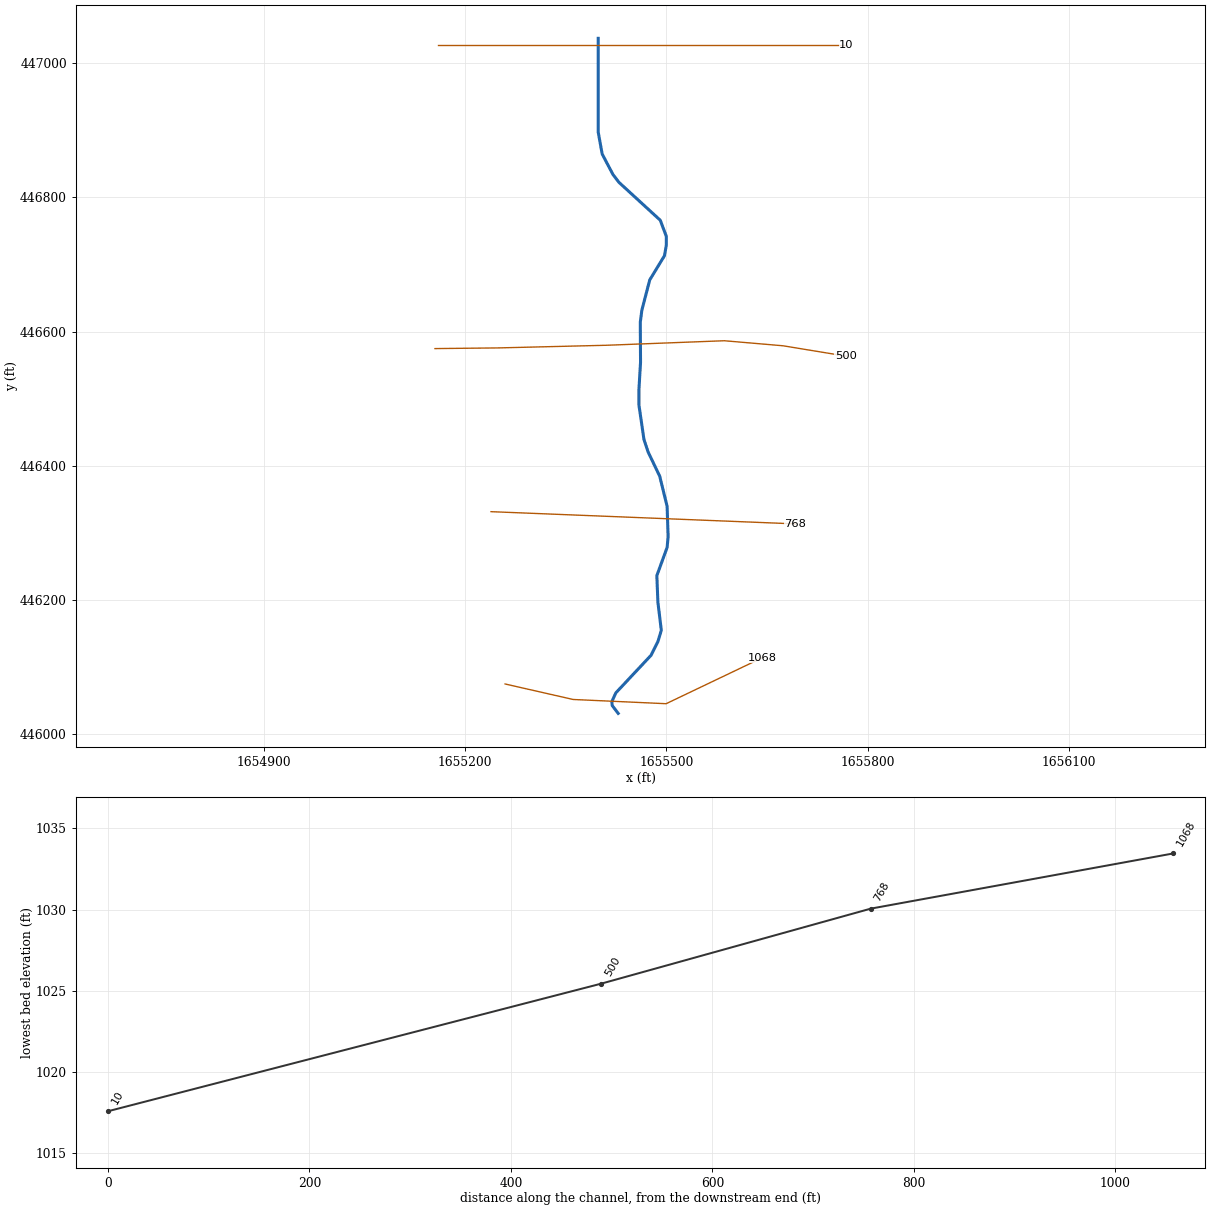
--- LTLAURELRN.prj (project) ---

Proj Title=LTLAURELRN
Current Plan=p01
Default Exp/Contr=0.3,0.1
English Units
Geom File=g01
Flow File=f01
Plan File=p01
Y Axis Title=Elevation
X Axis Title(PF)=Main Channel Distance
X Axis Title(XS)=Station
BEGIN DESCRIPTION:
---------- MODELED AS PART OF WVEMD CTP PROGRAM, 2023----------
Stream Name: Little Laurel Run
Flood Zone:  AFH
Wetzel County, WV
HEC-RAS Version: RAS 6.3
Vertical Datum: NAVD88
Projection: NAD 1983 StatePlane West Virginia S FIPS 4702 (US Feet)
Terrain: 1-meter West Virginia FEMA R3 South Central (collected 2018-2020)
Land Use: 2019 NLCD
Hydrologic Method:
WV 2010 Regional Regression Equations
Additional Model Notes:
None
END DESCRIPTION:
DSS Export Rating Curves= 0
DSS Export Rating Curve Sorted= 0
DSS Export Volume Flow Curves= 0
DXF OffsetX= 0
DXF OffsetY= 0
DXF ScaleX= 1
DXF ScaleY= 10

--- LTLAURELRN.p01 (plan) ---

Plan Title=Floodplain
Program Version=6.31
Short Identifier=Floodplain
Geom File=g01
Flow File=f01
Subcritical Flow
K Sum by GR= 0
Std Step Tol= 0.01
Critical Tol= 0.01
Num of Std Step Trials= 20
Max Error Tol= 0.3
Flow Tol Ratio= 0.001
Split Flow NTrial= 30
Split Flow Tol= 0.02
Split Flow Ratio= 0.02
Log Output Level= 0
Friction Slope Method= 1
Unsteady Friction Slope Method= 2
Unsteady Bridges Friction Slope Method= 1
Parabolic Critical Depth
Global Vel Dist= 0 , 0 , 0
Global Log Level= 0
CheckData=True
Encroach Param=-1 ,0,0, 0
Computation Interval=1MIN
Output Interval=1HOUR
Instantaneous Interval=1HOUR
Mapping Interval=1HOUR
Computation Time Step Use Courant=        0
Computation Time Step Use Time Series=    0
Computation Time Step Count To Double=0
Computation Time Step Max Doubling=0
Computation Time Step Max Halving=0
Computation Time Step Residence Courant=0
Run HTab= 0
Run UNet= 0
Run Sediment= 0
Run PostProcess= 0
Run WQNet= 0
Run RASMapper= 0
UNET Theta= 1
UNET Theta Warmup= 1
UNET ZTol= 0.02
UNET ZSATol= 0.02
UNET MxIter= 20
UNET Max Iter WO Improvement= 0
UNET MaxInSteps= 0
UNET DtIC= 0
UNET DtMin= 0
UNET MaxCRTS= 20
UNET WFStab= 2
UNET SFStab= 1
UNET WFX= 1
UNET SFX= 1
UNET Gravity=32.17405
UNET 1D Methodology=Finite Difference
UNET DSS MLevel= 4
UNET Pardiso=0
UNET DZMax Abort= 100
UNET Use Existing IB Tables=-1
UNET Froude Reduction=False
UNET Froude Limit= 0.8
UNET Froude Power= 4
UNET D1 Cores= 0
UNET WindReference=Eulerian
UNET WindDragFormulation=Hsu (1988)
UNET D2 Coriolis=0
UNET D2 Cores= 0
UNET D2 Theta= 1
UNET D2 Theta Warmup= 1
UNET D2 Z Tol= 0.01
UNET D2 Volume Tol= 0.01
UNET D2 Max Iterations= 20
UNET D2 Equation= 0
UNET D2 RampUpFraction=0.1
UNET D2 TimeSlices= 1
UNET D2 Turbulence Formulation=None
UNET D2 Eddy Viscosity=0.3
UNET D2 Transverse Eddy Viscosity=0.1
UNET D2 Smagorinsky Mixing=0.05
UNET D2 BCVolumeCheck=0
UNET D2 Cores=0
UNET D2 SolverType=PARDISO (Direct)
UNET D2 Minimum Iterations= 3
UNET D2 Maximum Iterations= 30
UNET D2 Restart Number= 10
UNET D2 Relaxation Coeff=1.3
UNET D2 SOR Precondition Iterations= 10
UNET D2 ILUT Maximum Fill= 8
UNET D2 ILUT Tolerance=1E-08
UNET D2 Convergence Tolerance=0.00001
UNET D1D2 MaxIter= 0
UNET D1D2 ZTol=0.01
UNET D1D2 QTol=0.1
UNET D1D2 MinQTol=1
Write IC File= 0
Write IC File at Fixed DateTime=0
Write IC File at Sim End=0
Echo Input=False
Echo Parameters=False
Echo Output=False
Write Detailed= 0
HDF Write Warmup=0
HDF Write Time Slices=0
HDF Flush=0
HDF Compression= 1
HDF Chunk Size= 1
HDF Spatial Parts= 1
HDF Use Max Rows=0
HDF Fixed Rows= 1
Calibration Method= 0
Calibration Iterations= 20
Calibration Max Change=0.05
Calibration Tolerance=0.2
Calibration Maximum=1.5
Calibration Minimum=0.5
Calibration Optimization Method= 1
WQ AD Non Conservative
WQ ULTIMATE=-1
WQ Max Comp Step=1HOUR
WQ Output Interval=15MIN
WQ Output Selected Increments= 0
WQ Create Restart=0
WQ Fixed Restart=0
WQ System Summary=0
WQ Write To DSS=0
Sorting and Armoring Iterations= 10
XS Update Threshold= 0.02
Bed Roughness Predictor= 0
Hydraulics Update Threshold= 0.02
Energy Slope Method= 1
Volume Change Method= 1
Sediment Retention Method= 0
Sediment TS Multiplier= 1
Warm Up Method= 0
XS Weighting Method= 0
Number of US Weighted Cross Sections= 1
Number of DS Weighted Cross Sections= 1
Upstream XS Weight=0
Main XS Weight=1
Downstream XS Weight=0
Number of DS XS's Weighted with US Boundary= 1
Upstream Boundary Weight= 1
Weight of XSs Associated with US Boundary= 0
Number of US XS's Weighted with DS Boundary= 1
Downstream Boundary Weight= 0.5
Weight of XSs Associated with DS Boundary= 0.5
Percentile Method= 0
Sediment Output Level= 3
Mass or Volume Output= 0
Output Increment Type= 1
Profile and TS Output Increment= 1
Transport Output Increment 1
XS Output Flag= 0
XS Output Increment= 10
Read HDF5 Sediment Hotstart= 0
Sediment Hotstart Type= 0
Write Gradation File= 0
Read Gradation Hotstart= 0
Write HDF5 File= 1
Write Binary Output= 1
Write DSS Sediment File= 0
DSS Sediment Output Type= 1
SV Curve= 0
Specific Gage Flag= 0
Subcell Erosion Methods= 0
Subcell Deposition Methods= 0
Advection Scheme= 1
Matrix Solver= 0
Implicit Weighting Factor= 1
Maximum Outer Loop Convergence Iterations= 5
Convergence Maximum Absolute= 0.001
Convergence RMSE= 0.0001
Grain Fractions Max Abs Error= 0.001
Max Subgrid Regions= 1
Max Subgrid Length Scale= 3.402823E+38
Initial Layer Thickness= 3.402823E+38
Min Layer Thickness= 3.402823E+38
Max Layer Thickness= 3.402823E+38
Number of Layers= 5

--- LTLAURELRN.f01 (steady flow) ---

Flow Title=Flow
Program Version=6.31
Number of Profiles= 1
Profile Names=F01pct
River Rch & RM=LTLAURELRN,Main,1068
     614
Boundary for River Rch & Prof#=LTLAURELRN,Main            , 1
Up Type= 0
Dn Type= 3
Dn Slope=0.01612
DSS Import GetInterval= 0
DSS Import GetPeak= 0
DSS Import FillOption= 0

--- LTLAURELRN.g01 (geometry) ---

Geom Title=Geometry
Program Version=6.30

River Reach=LTLAURELRN      ,Main
Reach XY= 30
 1655428.0328438446030.9979996381655419.02400355446042.748632312
1655418.63260014446048.6236205551655424.50758839 446061.54944773
1655476.99337581 446117.560162471655487.17708246446137.927575812
 1655492.2689358446154.7700618061655487.17708246446196.680082977
1655485.61048456446236.2403713171655500.88604455446278.150392473
1655502.45264247 446294.209415481655500.88604455446339.644692063
1655489.91887489446384.2968337241655472.68465739446420.331538558
1655466.41793764446439.132353976 1655458.9756953446490.051215395
 1655458.9756953 446514.72734715 1655461.3260843446554.287307397
 1655460.9343528446613.8232775631655463.28441373446631.840958059
1655475.03504638446676.8845031411655496.96905763446712.919207975
1655499.71085006446728.5868275611655499.71085006446741.904058144
1655490.70233789446765.796726897 1655429.2080383446822.199173138
1655420.19919805446833.9494777321655404.14017506446864.500925809
1655398.26485872 446897.010703311655398.26485872447036.841788471

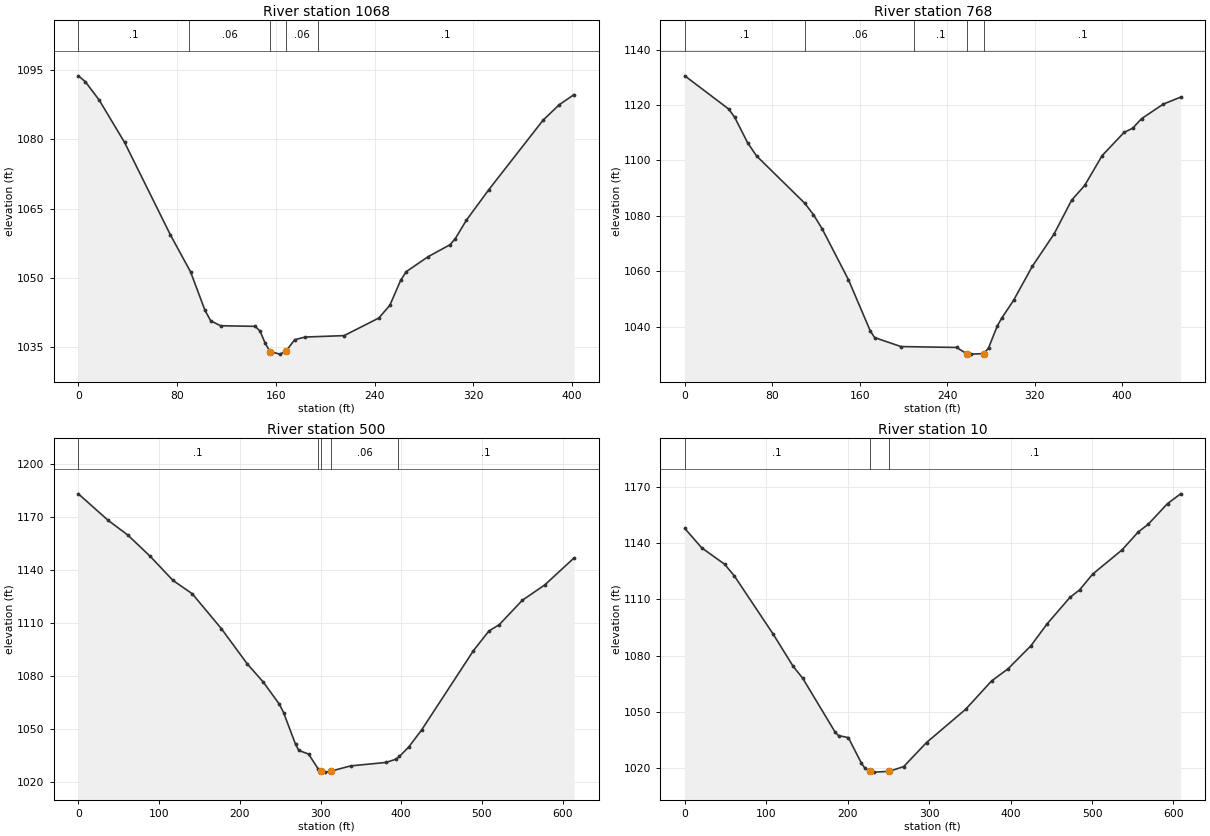
Type RM Length L Ch R = 1 ,1068    ,299.8,300.4,300.5
XS GIS Cut Line= 4
1655259.50449995446074.7942615971655360.94576915446051.707627916
1655499.46557124446045.4112732761655642.88253805446113.971579359
#Sta/Elev= 30
       0 1093.75     5.7 1092.48      17 1088.45    37.5 1079.31    74.5 1059.34
    90.9 1051.29   102.6 1042.95   107.2 1040.69   115.2 1039.61   143.2 1039.48
   147.2 1038.47   151.3 1035.85   155.3 1034.01   163.3 1033.46  167.94 1034.03
   175.3 1036.59   183.7 1037.16   215.3 1037.47   243.4 1041.28   252.3 1044.02
   261.2  1049.5   265.6 1051.32   283.3 1054.56   301.1 1057.16   305.4  1058.5
   314.4 1062.49   332.5 1069.08   376.4 1084.12   389.7 1087.52401.6601  1089.7
#Mann= 5 ,-1,0
       0      .1       0      90     .06       0   155.3    .045       0
  167.94     .06       0  194.04      .1       0
Bank Sta=155.3,167.94
XS Rating Curve= 0 ,0
Exp/Cntr(USF)=0,0
Exp/Cntr=0.3,0.1

Type RM Length L Ch R = 1 ,768     ,266.9,267.6,268.6
XS GIS Cut Line= 2
1655238.51665115446331.5456119311655691.85418525 446313.35614297
#Sta/Elev= 30
       0 1130.58    40.2 1118.58    45.6 1115.63    57.6 1106.32    65.7 1101.64
   109.7 1084.59   117.7 1080.45   125.7 1075.31   149.7 1056.98   169.7 1038.47
   173.7 1036.03   197.8 1032.79   248.8 1032.47   257.8 1030.21   261.8 1030.06
   273.8 1030.25     278 1032.36   285.8 1040.09   289.8 1042.94   300.8 1049.47
   317.9 1061.72   337.9 1073.46   353.9 1085.63   365.9 1090.99   381.9 1101.77
   401.9 1110.12   409.9 1111.69   417.9 1115.09   437.9 1120.38   453.7 1122.88
#Mann= 5 ,-1,0
       0      .1       0     110     .06       0     210      .1       0
   257.8    .045       0   273.8      .1       0
Bank Sta=257.8,273.8
XS Rating Curve= 0 ,0
Exp/Cntr(USF)=0,0
Exp/Cntr=0.3,0.1

Type RM Length L Ch R = 1 ,500     ,490.6,489.8,487.3
XS GIS Cut Line= 6
1655155.03437409446574.5497340861655248.81535451446575.551044419
1655411.28287734446579.5188842561655586.15359059 446586.24524875
1655673.73970151446578.7255787551655767.42881858446563.323378593
#Sta/Elev= 30
       0 1183.18    37.1 1168.09    61.1 1159.89    89.1 1147.74   117.1 1134.15
   141.1 1126.56   177.1 1106.82   209.1 1086.89   229.1 1076.48   249.1 1063.89
   254.2 1059.23   269.1 1041.19   273.1 1037.74   285.2 1035.68   297.2  1027.2
  300.34 1026.05   305.2 1025.44   313.2 1026.03   337.2 1028.97   381.2 1030.94
   393.2 1032.73   397.7 1034.33   409.2 1039.64   425.3 1049.38   489.5 1094.35
   508.6 1105.41   521.6  1109.1     550 1122.87   577.7 1131.51   614.2 1146.91
#Mann= 5 ,-1,0
       0      .1       0   296.3     .06       0  300.34    .045       0
   313.2     .06       0   396.3      .1       0
Bank Sta=300.34,313.2
XS Rating Curve= 0 ,0
Exp/Cntr(USF)=0,0
Exp/Cntr=0.3,0.1

Type RM Length L Ch R = 1 ,10      ,,,
XS GIS Cut Line= 2
1655159.34243214447026.6401069641655768.16618141447026.640106964
#Sta/Elev= 30
       0    1148    20.8 1137.62    48.8 1128.88    60.8 1122.62   108.8 1091.25
   132.8 1074.37   144.8 1067.81   184.8 1038.84   188.8 1037.15   200.8 1036.05
   216.8 1022.44   220.8 1019.89  226.79    1018   232.8 1017.58  250.86    1018
   268.8 1020.55   296.8 1033.42   344.8 1051.19   376.8 1066.44   396.8 1072.85
   424.8 1085.12   444.8  1096.9   472.8 1111.05   484.8 1115.15   500.8 1123.56
   536.8 1136.49   556.8 1146.13   568.8 1150.15   592.8 1161.33   608.8 1166.53
#Mann= 3 ,-1,0
       0      .1       0  226.79    .045       0  250.86      .1       0
Bank Sta=226.79,250.86
XS Rating Curve= 0 ,0
Exp/Cntr(USF)=0,0
Exp/Cntr=0.3,0.1
LCMann Table=0

Chan Stop Cuts=-1
Use User Specified Reach Order=0
Composite Channel Slope=5